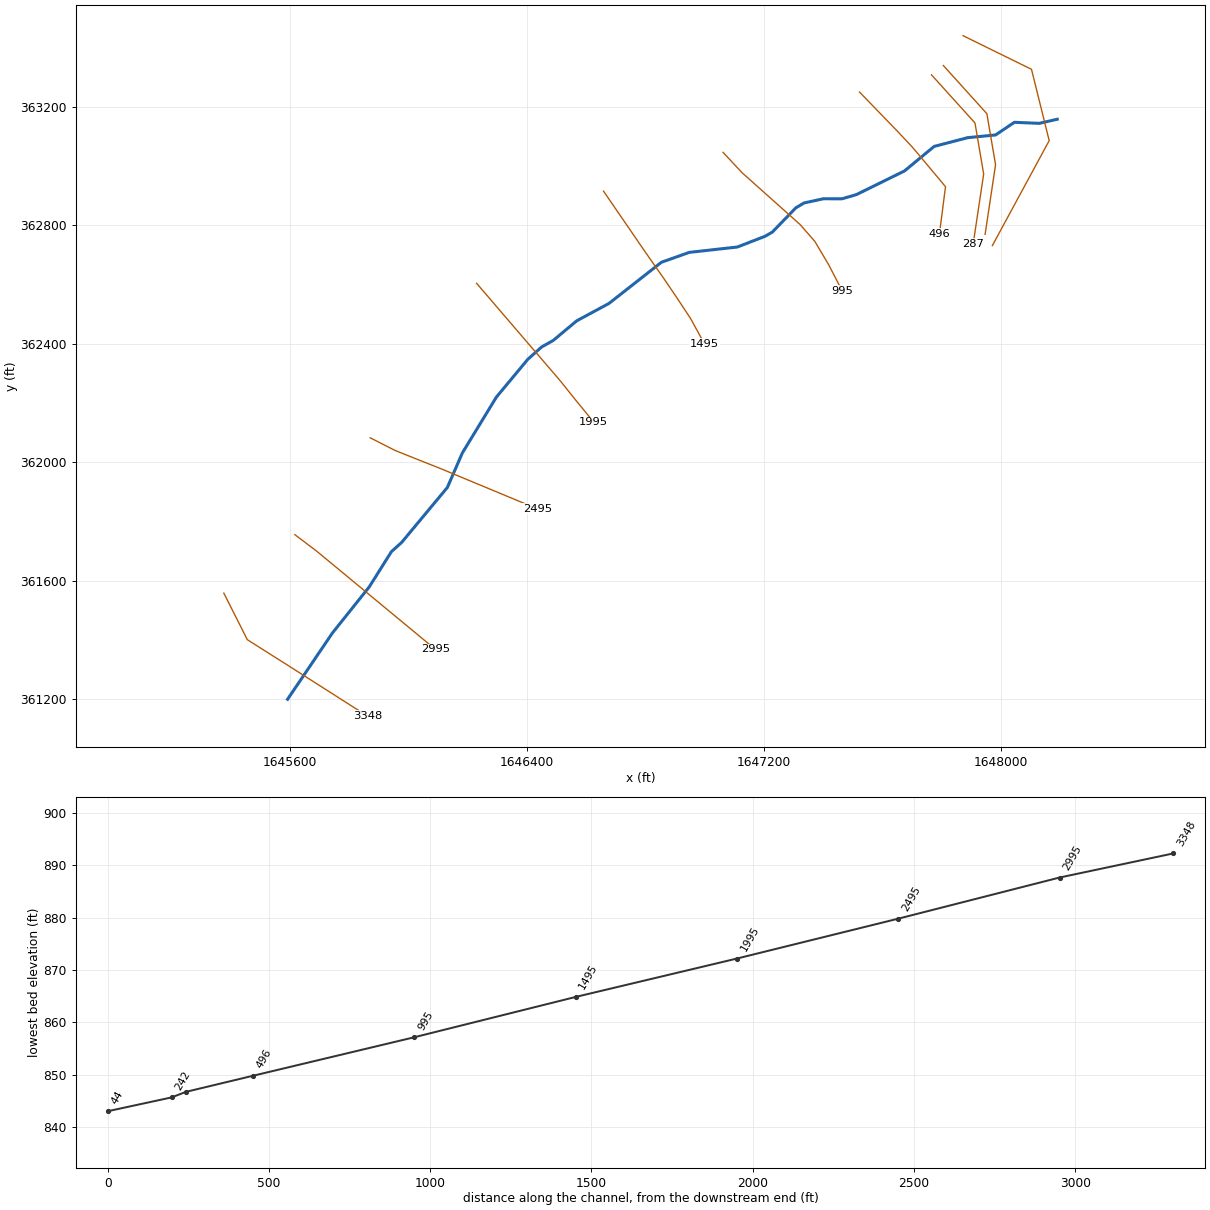
--- BUFALORNT3.prj (project) ---

Proj Title=BUFALORNT3
Current Plan=p01
Default Exp/Contr=0,0
English Units
Geom File=g01
Flow File=f01
Plan File=p01
BEGIN DESCRIPTION:
---------- MODELED AS PART OF WVEMD CTP PROGRAM, 2023----------
Stream Name: Buffalo Run Tributary 3
Flood Zone:  AFH
Wetzel County, WV
HEC-RAS Version: RAS 6.3
Vertical Datum: NAVD88
Projection: NAD 1983 StatePlane West Virginia S FIPS 4702 (US Feet)
Terrain: 1-meter West Virginia FEMA R3 South Central (collected 2018-2020)
Land Use: 2019 NLCD
Hydrologic Method:
WV 2010 Regional Regression Equations
Additional Model Notes:
None
END DESCRIPTION:
DSS Export Rating Curves= 0
DSS Export Rating Curve Sorted= 0
DSS Export Volume Flow Curves= 0
DXF OffsetX= 0
DXF OffsetY= 0
DXF ScaleX= 0
DXF ScaleY= 0

--- BUFALORNT3.p01 (plan) ---

Plan Title=Floodplain
Program Version=6.30
Short Identifier=Floodplain
Geom File=g01
Flow File=f01
Subcritical Flow
K Sum by GR= 0
Std Step Tol= 0.01
Critical Tol= 0.01
Num of Std Step Trials= 20
Max Error Tol= 0.3
Flow Tol Ratio= 0.001
Split Flow NTrial= 30
Split Flow Tol= 0.02
Split Flow Ratio= 0.02
Log Output Level= 0
Friction Slope Method= 1
Unsteady Friction Slope Method= 2
Unsteady Bridges Friction Slope Method= 1
Parabolic Critical Depth
Global Vel Dist= 0 , 0 , 0
Global Log Level= 0
CheckData=True
Encroach Param=-1 ,0,0, 0
Mapping Interval=1HOUR
Computation Time Step Use Courant=        0
Computation Time Step Use Time Series=    0
Computation Time Step Count To Double=0
Computation Time Step Max Doubling=0
Computation Time Step Max Halving=0
Computation Time Step Residence Courant=0
Run HTab= 0
Run UNet= 0
Run Sediment= 0
Run PostProcess= 0
Run WQNet= 0
Run RASMapper=-1
UNET Theta= 0
UNET Theta Warmup= 0
UNET ZTol= 0
UNET ZSATol= 0
UNET MxIter= 0
UNET Max Iter WO Improvement= 0
UNET MaxInSteps= 0
UNET DtIC= 0
UNET DtMin= 0
UNET MaxCRTS= 0
UNET WFStab= 0
UNET SFStab= 0
UNET WFX= 1
UNET SFX= 1
UNET Gravity=32.17405
UNET 1D Methodology=Finite Difference
UNET DSS MLevel= 1
UNET Pardiso=0
UNET DZMax Abort= 0
UNET Use Existing IB Tables= 0
UNET Froude Reduction=False
UNET Froude Limit= 0
UNET Froude Power= 0
UNET D1 Cores= 0
UNET WindReference=Eulerian
UNET WindDragFormulation=Hsu (1988)
UNET D2 Coriolis=0
UNET D2 Cores= 0
UNET D2 Theta= 1
UNET D2 Theta Warmup= 1
UNET D2 Z Tol= 0.01
UNET D2 Volume Tol= 0.01
UNET D2 Max Iterations= 20
UNET D2 Equation= 0
UNET D2 RampUpFraction=0.1
UNET D2 TimeSlices= 1
UNET D2 Turbulence Formulation=Non-Conservative (original)
UNET D2 Eddy Viscosity=0.3
UNET D2 Transverse Eddy Viscosity=0.1
UNET D2 Smagorinsky Mixing=0
UNET D2 BCVolumeCheck=0
UNET D2 Cores=0
UNET D2 SolverType=PARDISO (Direct)
UNET D2 Minimum Iterations= 3
UNET D2 Maximum Iterations= 30
UNET D2 Restart Number= 10
UNET D2 Relaxation Coeff=1.3
UNET D2 SOR Precondition Iterations= 10
UNET D2 ILUT Maximum Fill= 8
UNET D2 ILUT Tolerance=1E-08
UNET D2 Convergence Tolerance=0.00001
UNET D1D2 MaxIter= 0
UNET D1D2 ZTol=0.01
UNET D1D2 QTol=0.1
UNET D1D2 MinQTol=1
Write IC File= 0
Write IC File at Fixed DateTime=0
Write IC File at Sim End=0
Echo Input=False
Echo Parameters=False
Echo Output=False
Write Detailed= 0
HDF Write Warmup=0
HDF Write Time Slices=0
HDF Flush=0
HDF Compression= 1
HDF Chunk Size= 1
HDF Spatial Parts= 1
HDF Use Max Rows=0
HDF Fixed Rows= 1
Calibration Method= 0
Calibration Iterations= 20
Calibration Max Change=0.05
Calibration Tolerance=0.2
Calibration Maximum=1.5
Calibration Minimum=0.5
Calibration Optimization Method= 1
WQ AD Non Conservative
WQ ULTIMATE=-1
WQ Max Comp Step=1HOUR
WQ Output Interval=15MIN
WQ Output Selected Increments= 0
WQ Output face flow=0
WQ Output face velocity=0
WQ Output face area=0
WQ Output face dispersion=0
WQ Output cell volume=0
WQ Output cell surface area=0
WQ Output cell continuity=0
WQ Output cumulative cell continuity=0
WQ Output face conc=0
WQ Output face dconc_dx=0
WQ Output face courant=0
WQ Output face peclet=0
WQ Output face adv mass=0
WQ Output face disp mass=0
WQ Output cell mass=0
WQ Output cell source sink temp=0
WQ Output nsm pathways=0
WQ Output nsm derived pathways=0
WQ Create Restart=0
WQ Fixed Restart=0
WQ System Summary=0
WQ Write To DSS=0
Sorting and Armoring Iterations= 10
XS Update Threshold= 0.02
Bed Roughness Predictor= 0
Hydraulics Update Threshold= 0.02
Energy Slope Method= 1
Volume Change Method= 1
Sediment Retention Method= 0
Sediment TS Multiplier= 1
Warm Up Method= 0
XS Weighting Method= 0
Number of US Weighted Cross Sections= 1
Number of DS Weighted Cross Sections= 1
Upstream XS Weight=0
Main XS Weight=1
Downstream XS Weight=0
Number of DS XS's Weighted with US Boundary= 1
Upstream Boundary Weight= 1
Weight of XSs Associated with US Boundary= 0
Number of US XS's Weighted with DS Boundary= 1
Downstream Boundary Weight= 0.5
Weight of XSs Associated with DS Boundary= 0.5
Percentile Method= 0
Sediment Output Level= 3
Mass or Volume Output= 0
Output Increment Type= 1
Profile and TS Output Increment= 1
Transport Output Increment 1
XS Output Flag= 0
XS Output Increment= 10
Read HDF5 Sediment Hotstart= 0
Sediment Hotstart Type= 0
Write Gradation File= 0
Read Gradation Hotstart= 0
Write HDF5 File= 1
Write Binary Output= 1
Write DSS Sediment File= 0
DSS Sediment Output Type= 1
SV Curve= 0
Specific Gage Flag= 0
Subcell Erosion Methods= 0
Subcell Deposition Methods= 0
Advection Scheme= 1
Matrix Solver= 0
Implicit Weighting Factor= 1
Maximum Outer Loop Convergence Iterations= 5
Convergence Maximum Absolute= 0.001
Convergence RMSE= 0.0001
Grain Fractions Max Abs Error= 0.001
Max Subgrid Regions= 1
Max Subgrid Length Scale= 3.402823E+38
Initial Layer Thickness= 3.402823E+38
Min Layer Thickness= 3.402823E+38
Max Layer Thickness= 3.402823E+38
Number of Layers= 5

--- BUFALORNT3.f01 (steady flow) ---

Flow Title=Flow
Program Version=6.31
Number of Profiles= 1
Profile Names=F01pct
River Rch & RM=BUFALORNT3,Main,3348
     647
River Rch & RM=BUFALORNT3,Main,1995
     761
Boundary for River Rch & Prof#=BUFALORNT3,Main            , 1
Up Type= 0
Dn Type= 3
Dn Slope=0.01314
DSS Import GetInterval= 0
DSS Import GetPeak= 0
DSS Import FillOption= 0

--- BUFALORNT3.g01 (geometry) ---

Geom Title=Geometry
Program Version=6.30

River Reach=BUFALORNT3      ,Main
Reach XY= 30
     1645592.411      361200.008     1645744.023      361424.043
      1645868.32      361579.664     1645942.998      361698.448
     1645977.581      361729.522     1646131.949      361915.215
      1646182.57      362031.743     1646297.594      362220.444
     1646403.848      362348.248     1646449.958      362389.346
     1646489.803        362411.9     1646568.992      362478.058
     1646677.751      362536.698     1646854.924       362675.78
     1646948.899       362709.11     1647111.035      362727.153
     1647204.258      362763.239     1647229.067      362777.272
     1647308.757      362859.468     1647336.323      362876.008
     1647402.481      362890.292     1647464.379      362890.041
     1647513.496      362904.3251647675.73283908362984.114484311
1647775.90741938363066.960948555     1647889.393      363096.534
1647983.18849231363105.609230771     1648046.769      363148.408
1648130.84422782363144.868216778     1648191.594      363158.749

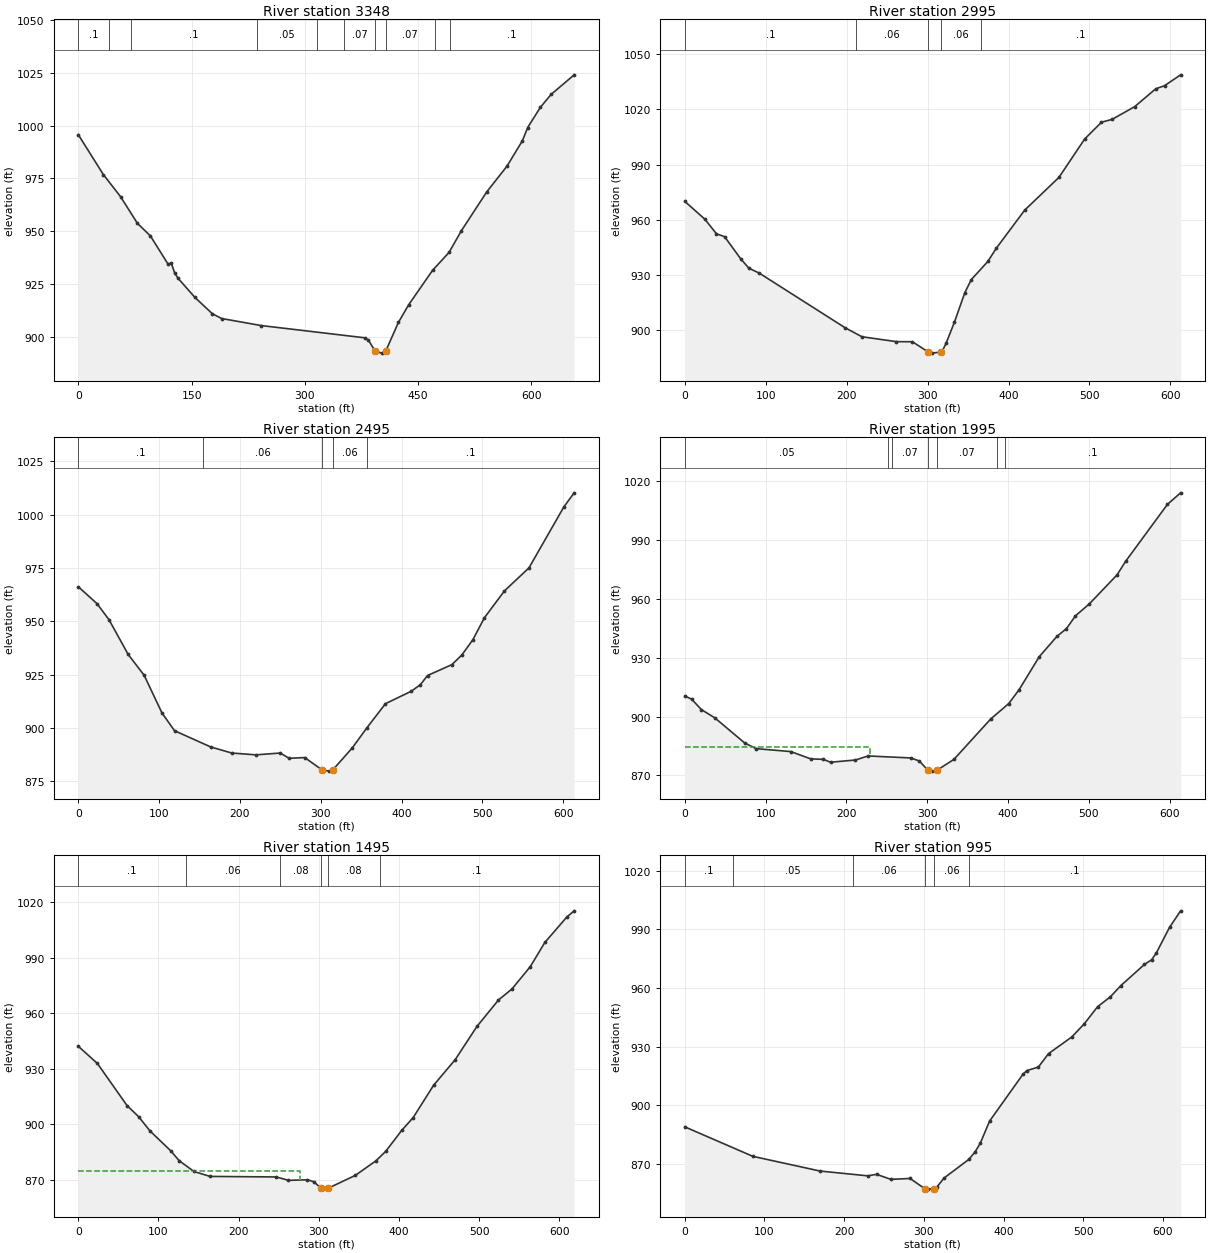
Type RM Length L Ch R = 1 ,3348    ,353.6,352.9,351.7
XS GIS Cut Line= 4
1645377.15064223361558.4126729411645456.38018061  361401.2964697
1645587.98178675361318.0383107181645861.92798727361143.464751561
#Sta/Elev= 30
       0  995.62    33.2  976.75    55.9  966.32    78.3  953.67    95.4  947.76
   118.6  934.52   123.1   934.8   127.5  930.27     132  927.72   154.4  918.63
   177.4  910.93   189.8  908.66   241.9  905.34   379.3  899.53     384  898.53
   392.6  893.42   401.5  892.28   407.2 893.395   423.8   906.8   437.2  915.06
     469  931.45   490.8  939.92   507.3  950.26   540.5  968.46   567.5  980.73
     588   992.8     595  999.05   611.7 1008.56   625.9 1014.68   656.5 1023.98
#Mann= 10, -1 ,  0
       0     0.1       0      40    0.08       0      70     0.1       0
  235.96    0.05       0  315.96     0.1       0  351.69    0.07       0
   392.6   0.045       0   407.2    0.07       0  471.69    0.06       0
  491.69     0.1       0
Bank Sta=392.6,407.2
XS Rating Curve= 0 ,0
Exp/Cntr(USF)=0,0
Exp/Cntr=0.3,0.1

Type RM Length L Ch R = 1 ,2995    ,498.1,500,501.9
XS GIS Cut Line= 6
1645616.94157368361756.0435184241645691.69273651361699.327424511
 1645759.1256725361643.5680215951645816.92444143361595.773825839
1645951.78801684361484.2530515041646091.46851176361368.750329763
#Sta/Elev= 30
       0  970.09    24.8  960.41    39.1  952.49    49.2  950.91    69.3  938.76
    79.3  933.75    91.8  931.18   198.2  901.42   218.9  896.56   261.4  893.91
   281.2  893.85     301888.2323   305.3  887.67     316  888.25   317.7  888.42
   322.8  892.98   333.1  904.44   345.9  920.41   353.9  927.57   374.4  937.45
     385  944.72     420  965.36   462.3  983.14     494 1003.94   514.8 1013.08
     528 1014.64   555.9 1021.57   581.9 1031.25   592.7 1032.91   612.6 1038.83
#Mann= 5, -1 ,  0
       0     0.1       0  211.33    0.06       0     301   0.045       0
     316    0.06       0  366.33     0.1       0
Bank Sta=301,316
XS Rating Curve= 0 ,0
Exp/Cntr(USF)=0,0
Exp/Cntr=0.3,0.1

Type RM Length L Ch R = 1 ,2495    ,502.5,500,496.7
XS GIS Cut Line= 6
1645871.53456843362082.9240982531645955.79522668362040.117097259
1646037.09296434362007.5390784291646106.85069884361979.960065335
1646199.18515985361941.5631605091646435.79262626361843.170312673
#Sta/Elev= 30
       0  966.25    23.1  958.35    37.9  950.84    61.7   934.5    81.4  924.78
   103.5  907.07     119  898.76   163.8  891.15   189.8   888.3   219.8  887.44
   249.9   888.3   260.7  885.83   280.1  886.17   301.5  880.38   310.5  879.81
   314.8  880.38   338.9  890.71   357.1  900.17     380  911.45   411.9  917.27
   423.1  920.32     432  924.64   462.1  929.74   474.4  934.24   488.1  941.45
   502.4  951.73   527.1   964.3   557.5  975.13   600.7 1003.73   613.4 1010.31
#Mann= 5, -1 ,  0
       0     0.1       0  154.51    0.06       0   301.5   0.045       0
   314.8    0.06       0   357.1     0.1       0
Bank Sta=301.5,314.8
XS Rating Curve= 0 ,0
Exp/Cntr(USF)=0,0
Exp/Cntr=0.3,0.1

Type RM Length L Ch R = 1 ,1995    ,500.9,500.6,499.7
XS GIS Cut Line= 6
1646230.67427009362604.7222672551646348.71766917362467.183828428
1646462.69021025362334.3881622551646511.53624117362277.473249838
1646566.30975367362208.9917595091646626.39165451362136.013887092
#Sta/Elev= 30
       0  910.48     8.4  908.93    20.6  903.55    37.1  899.38      74  886.58
    88.2  883.66   131.2  882.16   155.8  878.44   171.4   878.2   180.3  876.73
   211.1  877.86   226.9  879.93   279.6  878.91   290.2  877.36   300.5872.7729
     306  872.19   312.4 872.726     333  878.18   378.4  898.74   400.9  906.68
   413.7  913.76   438.6  930.57   460.8  941.07   472.2  944.84   483.4   951.4
   500.6  957.51   534.8  972.28   545.4  979.18   597.2 1008.27   613.5 1014.14
#Mann= 7, -1 ,  0
       0    0.05       0  251.25    0.06       0  256.25    0.07       0
   300.5   0.045       0   312.4    0.07       0  386.25    0.06       0
  396.25     0.1       0
#XS Ineff= 2 , 0
          228.97  884.62
Permanent Ineff=
       F       F
Bank Sta=300.5,312.4
XS Rating Curve= 0 ,0
Exp/Cntr(USF)=0,0
Exp/Cntr=0.3,0.1

Type RM Length L Ch R = 1 ,1495    ,497.3,499.4,500.9
XS GIS Cut Line= 6
1646659.21573584362916.157339916 1646804.1275195362704.817539498
1646861.65266693362622.9269552531646904.52364418362559.703000337
1646953.69743034362485.2339891791647000.04412243362400.425759837
#Sta/Elev= 30
       0  942.15    23.8  932.84    60.8  910.06    75.2  904.05    89.6  896.25
   115.5   885.5   125.6  880.32   144.2  874.39   164.3  871.72   246.9  871.43
   262.2   869.6   285.9   869.9   293.8  868.83   302.7865.3864   305.5  864.84
   311.9  865.37   345.5  872.26   371.1   880.1   383.4  885.23   403.5  896.65
   417.7  903.53   443.4  921.15   470.1  934.86   497.3  952.88   524.2  967.21
     541  973.17   563.8  985.21     582  998.33   609.4 1012.08   618.6 1015.46
#Mann= 6, -1 ,  0
       0     0.1       0  133.75    0.06       0  251.25    0.08       0
   302.7   0.045       0   311.9    0.08       0  376.33     0.1       0
#XS Ineff= 2 , 0
          276.28  874.91
Permanent Ineff=
       F       F
Bank Sta=302.7,311.9
XS Rating Curve= 0 ,0
Exp/Cntr(USF)=0,0
Exp/Cntr=0.3,0.1

Type RM Length L Ch R = 1 ,995     ,500.6,499.2,497.3
XS GIS Cut Line= 6
1647062.98822226363047.018298671  1647127.085535362978.254984751
   1647322.89223362803.4239695821647372.79173651362746.527101755
1647419.47701059362667.8241751791647464.83256292362580.267263666
#Sta/Elev= 30
       0  889.01    85.4  873.92   169.6  866.41   229.4  863.95   240.7   864.7
   258.7  862.16   282.8   862.6   300.9  857.45   305.6  857.15   312.8  857.45
   316.9  858.48   325.4  862.83   356.5  872.36   364.4  876.25   370.8  880.59
   382.6     892   424.6  916.01   429.5  917.81   443.8  919.59   456.5  926.46
   485.7  934.97   501.4  941.73   518.2  950.51   533.8  955.38   547.4   961.3
   576.9  972.08     586  974.47   591.9  978.03   608.5  991.11   622.3   999.5
#Mann= 6, -1 ,  0
       0     0.1       0      60    0.05       0   211.5    0.06       0
   300.9   0.045       0   312.8    0.06       0   356.5     0.1       0
Bank Sta=300.9,312.8
XS Rating Curve= 0 ,0
Exp/Cntr(USF)=0,0
Exp/Cntr=0.3,0.1

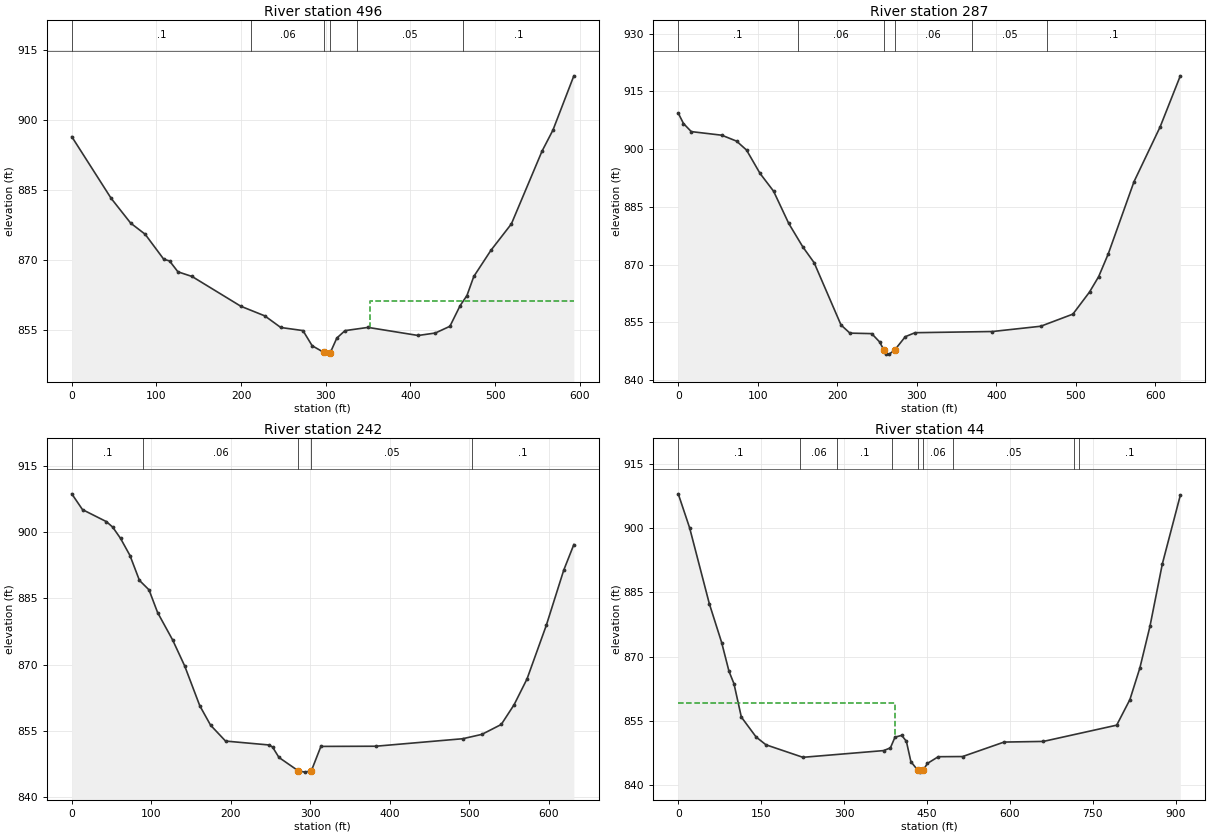
Type RM Length L Ch R = 1 ,496     ,211.2,209,206.5
XS GIS Cut Line= 6
1647523.78913793363250.6113954191647650.24131285363119.923336595
 1647701.8265115363065.1078294221647766.18661901362988.540069178
1647814.20817651 362930.951273591647793.73673262362771.326165985
#Sta/Elev= 30
       0  896.35    46.5  883.15    69.6  877.84    86.7  875.46   108.7   870.1
   115.5  869.75   125.4  867.42   142.1  866.42   199.7  860.05     228  857.99
   246.9   855.5   273.1  854.84     284  851.59     298  850.15   304.2   849.8
   305.4 850.116   313.1  853.24   322.8  854.83     350  855.52   409.2  853.79
   429.5  854.32   446.7  855.76   458.8  860.19   466.8  862.33   474.9  866.42
   495.1  872.01   519.3  877.67   555.5  893.24   568.4  897.75   593.1  909.37
#Mann= 6, -1 ,  0
       0     0.1       0  211.85    0.06       0     298   0.045       0
   305.4    0.06       0  337.12    0.05       0  462.13     0.1       0
#XS Ineff= 2 , 0
                           352.2           861.1
Permanent Ineff=
       F       F
Bank Sta=298,305.4
XS Rating Curve= 0 ,0
Exp/Cntr(USF)=0,0
Exp/Cntr=0.3,0.1

Type RM Length L Ch R = 1 ,287     ,44.9,45,45.2
XS GIS Cut Line= 4
  1647766.904208363308.6992629091647913.74742873363146.192765311
1647943.11607287362973.896719664 1647907.8736999 362738.94756651
#Sta/Elev= 30
       0  909.37     6.6  906.66    16.4  904.56    54.8  903.62    73.4  902.08
    85.9  899.76   102.9  893.68   119.9  889.07     139  880.67   156.7  874.58
   170.9  870.48   204.7  854.29   215.9  852.17   243.3  852.04   253.2  849.89
   258.7847.7679   261.3  846.85   265.3  846.71     272  847.73   285.6  851.25
   297.8  852.28   395.2  852.59   455.9  853.96   496.3  857.11   517.2  862.85
   528.7  866.85   540.8  872.78   573.1  891.51     606  905.78   631.4  919.06
#Mann= 6, -1 ,  0
       0     0.1       0     150    0.06       0   258.7   0.045       0
     272    0.06       0  369.02    0.05       0   463.8     0.1       0
Bank Sta=258.7,272
XS Rating Curve= 0 ,0
Exp/Cntr(USF)=0,0
Exp/Cntr=0.3,0.1

Type RM Length L Ch R = 1 ,242     ,196.7,198,198.3
XS GIS Cut Line= 4
  1647807.041355363340.0258166631647953.88457572363177.519319065
1647983.25321987363005.2232734181647948.01084689362770.274120264
#Sta/Elev= 30
       0  908.72    13.5  905.14    43.4  902.43    51.4  901.19    61.3  898.63
    73.2  894.74    85.1   889.1    97.1  886.96     108  881.79   126.9  875.58
     142  869.71     161  860.68   174.6  856.27   193.4  852.68   248.4  851.79
   252.5  851.32   260.6  848.96   284.9  845.93   293.1  845.64   301.3  845.94
   313.3  851.47   382.3  851.51   491.6  853.21   515.8   854.2   540.1  856.44
   556.3  860.93   572.5  866.76   596.7  878.88   618.7  891.43   631.4  897.22
#Mann= 5, -1 ,  0
       0     0.1       0      90    0.06       0   284.9   0.045       0
   301.3    0.05       0   503.8     0.1       0
Bank Sta=284.9,301.3
XS Rating Curve= 0 ,0
Exp/Cntr(USF)=0,0
Exp/Cntr=0.3,0.1

Type RM Length L Ch R = 1 ,44      ,,,
XS GIS Cut Line= 4
1647873.61028173363440.8581615581648104.64361566  363327.2994042
1648164.35985876363086.4765222171647972.48471701362732.094882876
#Sta/Elev= 30
       0  907.99    20.6  900.05    56.3  882.31    78.6  873.25    91.9  866.52
   100.8  863.67   114.2  855.86     141  851.19   158.8  849.38   225.6  846.46
   371.6  848.03   383.9  848.66   392.2  851.16   404.4  851.59   412.8   850.2
     421  845.45   433.4  843.45   437.6     843   443.2843.4385   450.8  845.02
   470.5   846.6   514.5  846.64   589.6  850.02   660.6  850.17   793.4  853.97
   817.3  859.95   835.3  867.32   853.5  877.01     876  891.64   908.5  907.65
#Mann= 9, -1 ,  0
       0     0.1       0     220    0.06       0  287.43     0.1       0
  387.43    0.06       0   433.4   0.045       0   443.2    0.06       0
  497.43    0.05       0  715.55    0.06       0  725.55     0.1       0
#XS Ineff= 2 , 0
          392.07  859.04
Permanent Ineff=
       F       F
Bank Sta=433.4,443.2
XS Rating Curve= 0 ,0
Exp/Cntr(USF)=0,0
Exp/Cntr=0.3,0.1
LCMann Table=0

Chan Stop Cuts=-1
Use User Specified Reach Order=0
Composite Channel Slope=5